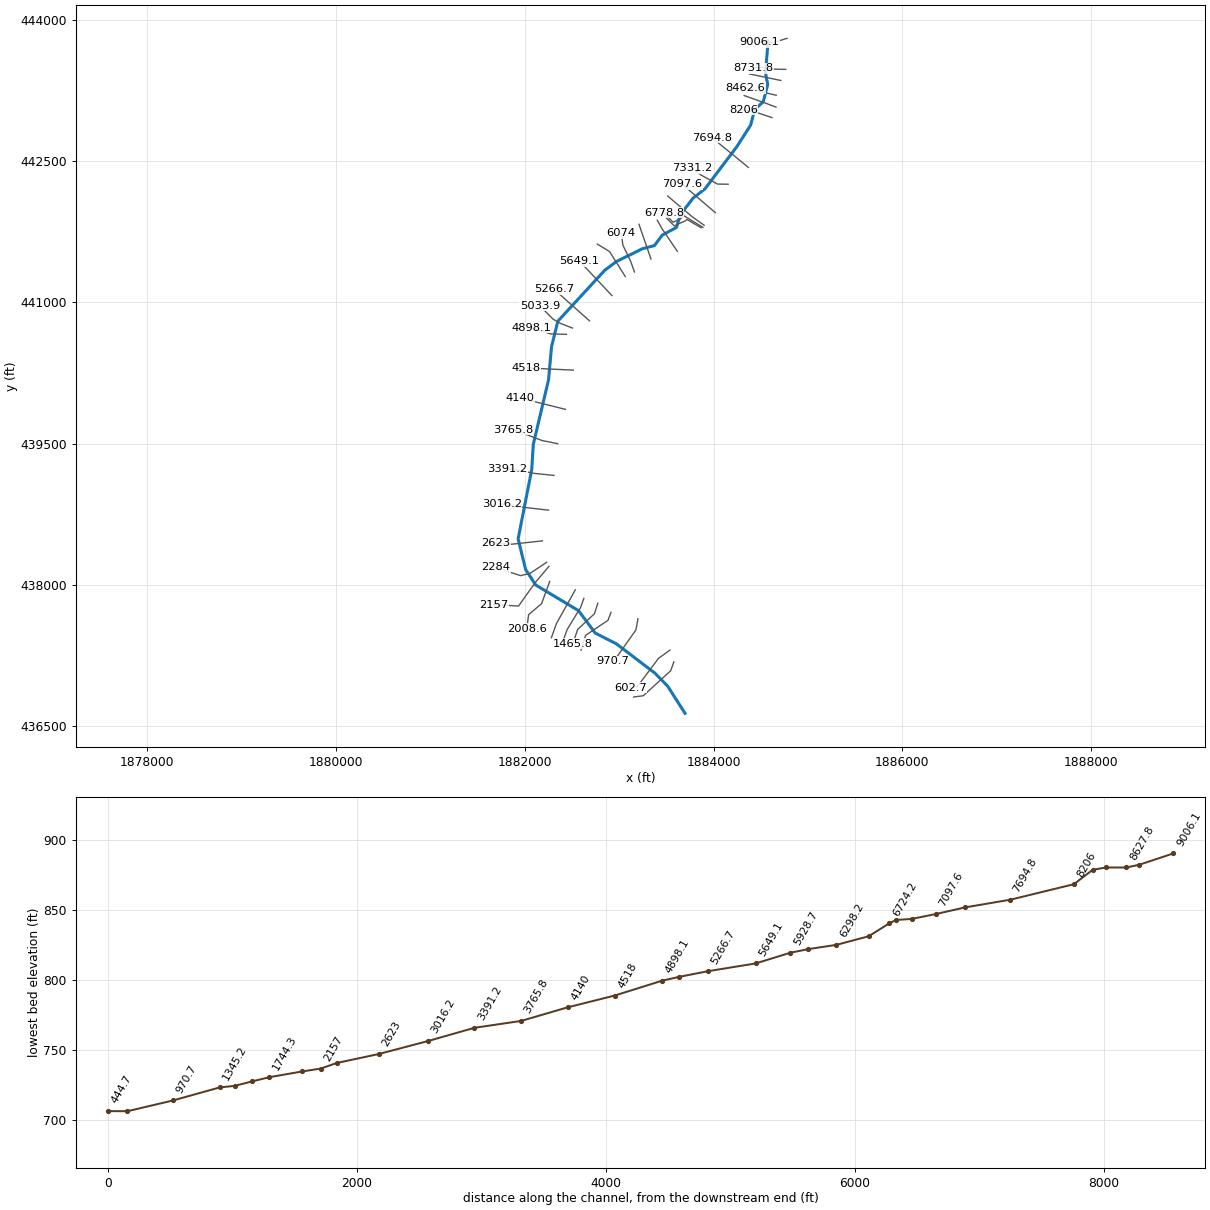
--- BULLPUSHFK.prj (project) ---

Proj Title=BULLPUSHFK
Current Plan=p01
Default Exp/Contr=0,0
English Units
Geom File=g01
Flow File=f01
Plan File=p01
BEGIN DESCRIPTION:
END DESCRIPTION:
DSS Export Rating Curves= 0
DSS Export Rating Curve Sorted= 0
DSS Export Volume Flow Curves= 0
DXF OffsetX= 0
DXF OffsetY= 0
DXF ScaleX= 0
DXF ScaleY= 0

--- BULLPUSHFK.p01 (plan) ---

Plan Title=Floodplain
Program Version=4.00
Geom File=g01
Flow File=f01
K Sum by GR=0
Std Step Tol=0.01
Critical Tol=0.01
Num of Std Step Trials=20
Max Error Tol=0.3
Flow Tol Ratio=0.001
Split Flow NTrial=30
Split Flow Tol=0.02
Split Flow Ratio=0.02
Log Output Level=0
Friction Slope Method=1
Unsteady Friction Slope Method=2
Unsteady Bridges Friction Slope Method=1
Global Log Level=0
CheckData=False
Run HTab=0
Run UNet=0
Run PostProcess=0
UNET Theta=0
UNET Theta Warmup=0
UNET ZTol=0
UNET ZSATol=0
UNET MxIter=0
UNET MaxInSteps=0
UNET DtIC=0
UNET DtMin=0
UNET MaxCRTS=0
UNET WFStab=0
UNET SFStab=0
UNET WFX=0
UNET SFX=0
UNET DSS MLevel=0
UNET DZMax Abort=0
UNET Convert EG Bridges=0
UNET Use Existing IB Tables=0
UNET Froude Limit=0
UNET Froude Power=0
Write IC File=0
Echo Input=False
Echo Output=False
Write Detailed=0

--- BULLPUSHFK.f01 (steady flow) ---

Flow Title=NFF Regression Equation
Program Version=4.10
Number of Profiles= 1
Profile Names=P100yr
River Rch & RM=BULLPUSHFK,Main            ,9006.1
816.5304
River Rch & RM=BULLPUSHFK,Main            ,8627.8
880.0769
River Rch & RM=BULLPUSHFK,Main            ,5928.7
936.8147
River Rch & RM=BULLPUSHFK,Main            ,5649.1
1081.488
River Rch & RM=BULLPUSHFK,Main            ,2284
1190.458
River Rch & RM=BULLPUSHFK,Main            ,2008.6
1329.619
River Rch & RM=BULLPUSHFK,Main            ,1744.3
1367.808
River Rch & RM=BULLPUSHFK,Main            ,444.7
1479.182
Boundary for River Rch & Prof#=BULLPUSHFK,Main            , 1
Up Type= 0
Dn Type= 3
Dn Slope=0.03
DSS Import GetInterval= 0
DSS Import GetPeak= 0
DSS Import FillOption= 0

--- BULLPUSHFK.g01 (geometry) ---

Geom Title=USGS 10m DEM
Program Version=4.10

River Reach=BULLPUSHFK      ,Main
Reach XY= 30
     1884578.111      443779.084      1884550.75      443435.905
     1884574.014      443314.464     1884526.488       443130.74
     1884436.696      443049.953     1884392.792      442883.272
     1884249.673       442658.85     1883909.569      442206.767
      1883784.83      442109.501     1883649.554      441935.335
     1883606.423      441796.198     1883455.793      441715.122
     1883373.306      441604.011     1883246.548      441570.591
     1882971.505      441435.521     1882847.156      441342.292
      1882349.76      440800.669     1882283.267      440531.745
     1882250.976      440177.405     1882089.764      439493.159
     1882073.251      439226.392     1881928.873      438489.684
     1882007.953      438165.075     1882115.157      437999.059
     1882568.065      437727.575     1882746.668      437488.426
     1882970.626      437374.276     1883382.301       437060.04
     1883514.246       436924.19      1883698.06      436635.853

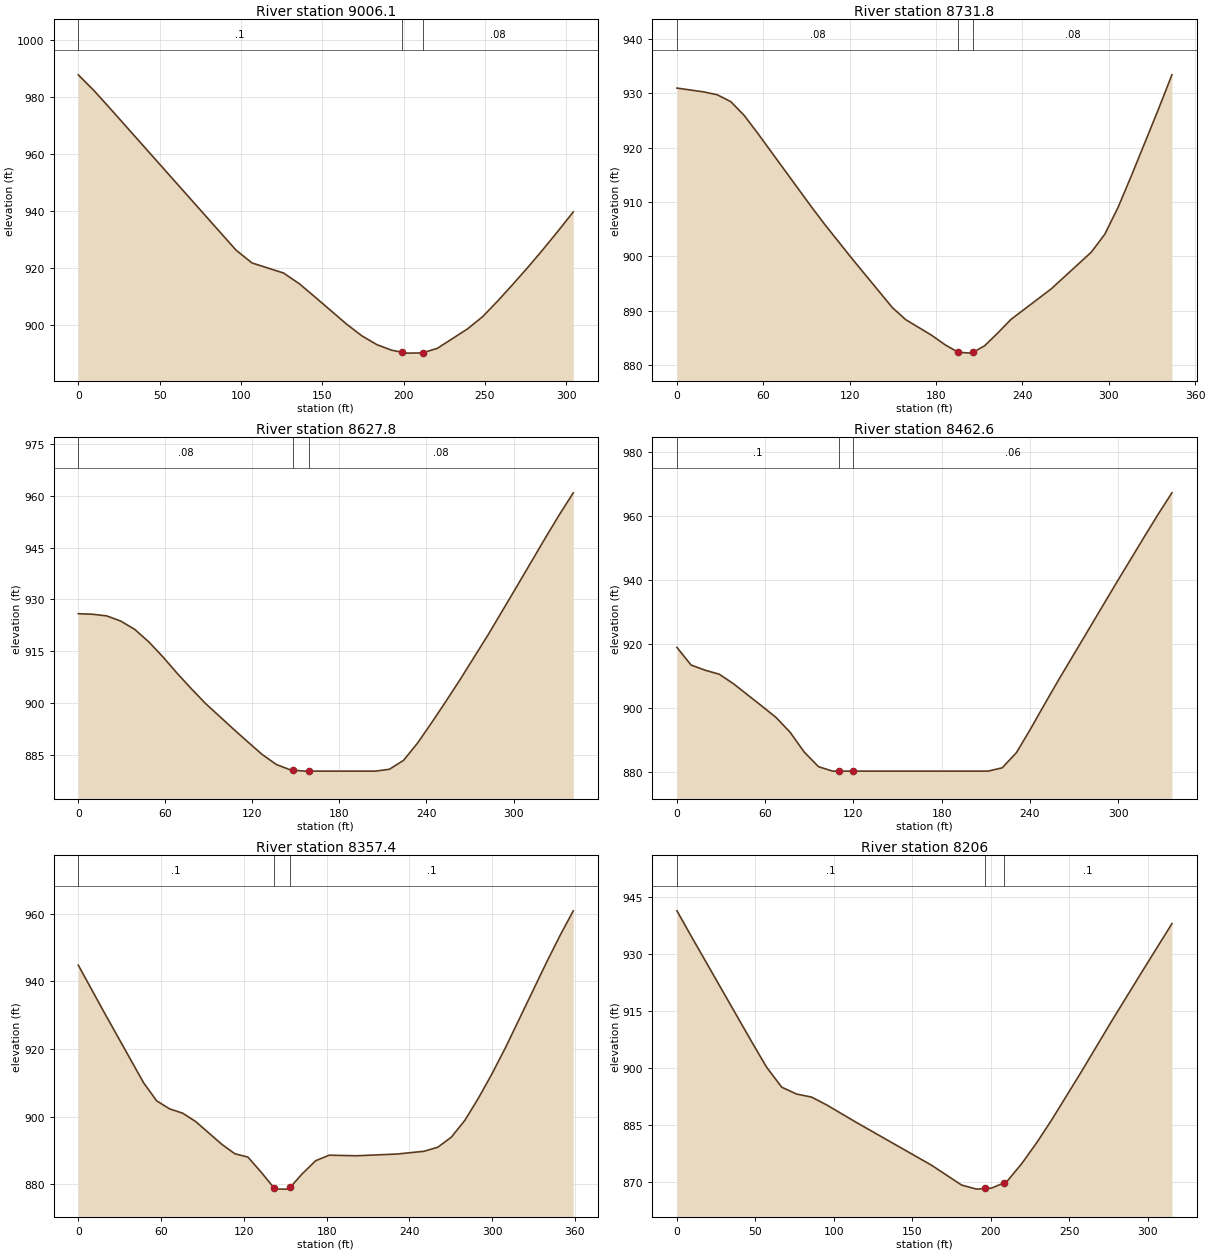
Type RM Length L Ch R = 1 ,9006.1  ,276.9,274.3,269.9
XS GIS Cut Line= 3
     1884779.362       443805.02     1884621.612        443756.7
     1884482.533      443764.206
#Sta/Elev= 25
       0  987.88     9.7  982.32    19.4   976.2      97  926.38   106.8   921.9
   126.2  918.36   135.9   914.6   145.6  909.93     165  900.42   174.3  896.35
   183.6  893.23   192.8  891.27     199 890.596     202  890.27   211.4  890.34
     212 890.443   220.7  891.94   239.3  898.77   248.6  903.07   257.8  908.52
   267.1  914.37   276.4  920.37   285.7  926.62     295  933.12   304.3  939.79
#Mann= 3 , 0 , 0
       0      .1       0     199    .045       0     212     .08       0
Bank Sta=199,212
XS Rating Curve= 0 ,0
Exp/Cntr=0.3,0.1

Type RM Length L Ch R = 1 ,8731.8  ,103,104,102.7
XS GIS Cut Line= 4
     1884765.256      443475.246     1884606.402      443478.718
     1884525.673      443495.211     1884423.242      443489.134
#Sta/Elev= 26
       0  930.99    18.7  930.28      28  929.76    37.4  928.49    46.7  925.96
    56.1  922.67    93.5  909.08   102.8  905.83   121.5  899.61   149.6  890.56
   158.9  888.33   177.2   885.4   186.4  883.67   195.5   882.3   204.7  882.15
   205.5  882.27   213.8  883.51     223  885.88   232.1  888.37     260  893.98
   287.9  900.76   297.3  904.07   306.6  909.08   315.9  914.94   334.6  927.14
   343.9  933.43
#Mann= 3 , 0 , 0
       0     .08       0   195.5    .045       0   205.5     .08       0
Bank Sta=195.5,205.5
XS Rating Curve= 0 ,0
Exp/Cntr=0.3,0.1

Type RM Length L Ch R = 1 ,8627.8  ,165.2,165.3,164.8
XS GIS Cut Line= 2
     1884712.738      443357.633     1884378.711      443427.076
#Sta/Elev= 30
       0  925.86     9.8   925.7    19.5  925.23    29.2  923.74      39  921.28
    48.7  917.65    58.5  913.26    68.2  908.55      78  904.07    87.7  899.82
   107.2   892.3     117  888.63   126.7  885.05   136.5  882.13   146.2  880.56
     148 880.494     156   880.2     159   880.2   204.7   880.2   214.4  880.73
   224.2  883.32   233.9  888.36   243.7  894.32   253.4  900.44   263.2  906.75
   282.7  919.88   302.2   933.7   321.7  947.65   331.4  954.43   341.2  960.91
#Mann= 3 , 0 , 0
       0     .08       0     148    .045       0     159     .08       0
Bank Sta=148,159
XS Rating Curve= 0 ,0
Exp/Cntr=0.3,0.1

Type RM Length L Ch R = 1 ,8462.6  ,107.5,105.2,102.5
XS GIS Cut Line= 2
     1884664.223      443200.351     1884336.775      443277.918
#Sta/Elev= 23
       0  918.91     9.6   913.4    19.2  911.77    28.8  910.52    38.5  907.52
    57.7  900.57    67.3  897.03    76.9  892.39    86.5  886.18    96.2   881.6
   105.8   880.2     110   880.2     120   880.2   211.5   880.2   221.1  881.23
   230.8  885.99   240.4  893.41     250   901.2   259.6  908.85     298  938.53
   317.3  953.21   326.9  960.41   336.5  967.28
#Mann= 3 , 0 , 0
       0      .1       0     110    .045       0     120     .06       0
Bank Sta=110,120
XS Rating Curve= 0 ,0
Exp/Cntr=0.3,0.1

Type RM Length L Ch R = 1 ,8357.4  ,147.5,151.4,153.5
XS GIS Cut Line= 3
     1884661.689      443074.465     1884546.807       443118.36
     1884324.553      443197.207
#Sta/Elev= 30
       0  944.75    18.9   930.7    47.3  910.02    56.8  904.65    66.2  902.28
    75.7     901    85.1  898.53   104.1  891.78   113.5  889.01     123  888.02
   132.8  883.45   141.7  879.02   142.6  878.57   152.5  878.56   153.7 879.116
   162.3  883.08   172.1  886.96   181.9  888.59   201.6  888.42   231.1  888.93
   250.7  889.75   260.6  890.94   270.4  893.91   280.2  898.88     290  905.41
   299.8  912.58   309.7   920.4   339.2  945.38     349  953.35   358.8   960.8
#Mann= 3 , 0 , 0
       0      .1       0   141.7    .045       0   153.7      .1       0
Bank Sta=141.7,153.7
XS Rating Curve= 0 ,0
Exp/Cntr=0.3,0.1

Type RM Length L Ch R = 1 ,8206    ,520.4,511.2,499.6
XS GIS Cut Line= 3
     1884618.562      442963.525     1884482.877      443008.834
     1884314.728      443046.862
#Sta/Elev= 23
       0  941.48     9.5  934.52    47.7  906.96    57.2  900.28    66.8  895.05
    76.3  893.25    85.8  892.45    95.4   890.4   114.4  885.77   162.2  874.53
   181.4   869.3   190.9  868.23   196.6 868.397   200.5  868.51   208.6   869.9
   210.1  870.16   219.7  874.94   229.2  880.43   238.8  886.46     258  899.34
   277.1  912.53   296.3  925.43   315.4   938.1
#Mann= 3 , 0 , 0
       0      .1       0   196.6    .045       0   208.6      .1       0
Bank Sta=196.6,208.6
XS Rating Curve= 0 ,0
Exp/Cntr=0.3,0.1

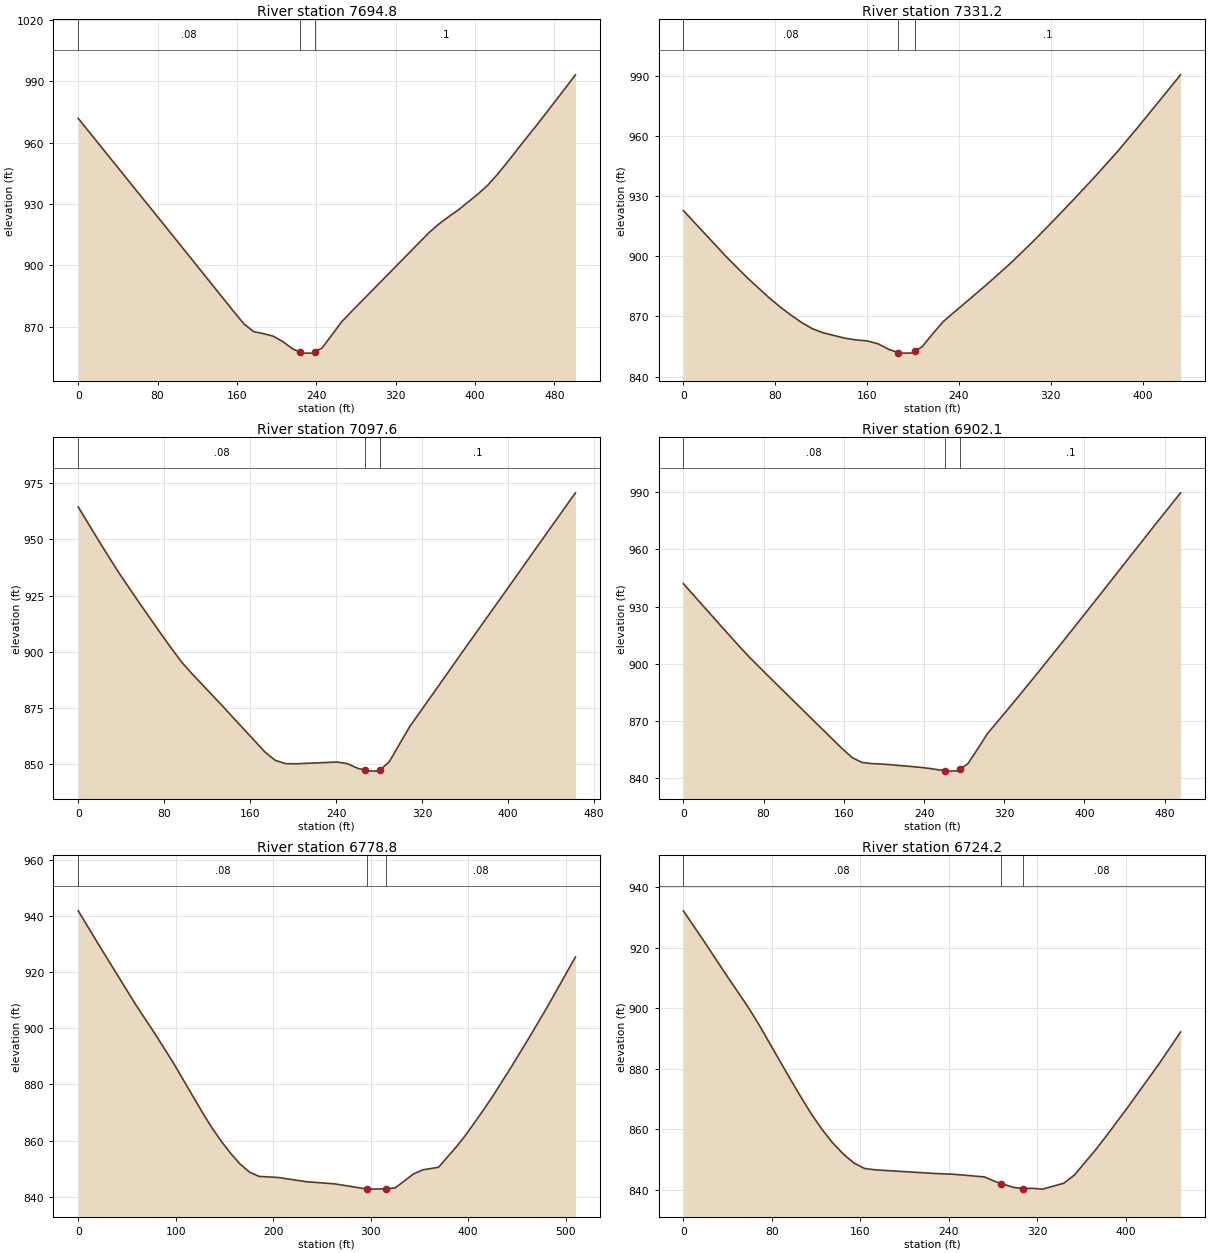
Type RM Length L Ch R = 1 ,7694.8  ,357.7,363.6,366.6
XS GIS Cut Line= 2
     1884369.182      442434.153     1883981.246      442751.717
#Sta/Elev= 29
       0  971.85    98.3  912.76   157.3  877.14   167.1   871.4   176.9  867.63
   186.8  866.66   196.6  865.43   206.4  862.72   216.3  859.18   223.2  857.74
   226.1  857.14   235.9  857.14   238.2  857.72   245.8  859.64   255.6  865.93
   265.4  872.36   275.2  877.33   353.9  916.15   363.7  920.28   373.6  923.87
   383.4   927.2     403   934.9   412.9  939.22   422.7  944.54   432.5  950.37
   452.2  962.52     462  968.41   491.5  986.92   501.3  993.17
#Mann= 3 , 0 , 0
       0     .08       0   223.2    .045       0   238.2      .1       0
Bank Sta=223.2,238.2
XS Rating Curve= 0 ,0
Exp/Cntr=0.3,0.1

Type RM Length L Ch R = 1 ,7331.2  ,237.3,233.6,227.9
XS GIS Cut Line= 4
     1884154.565      442255.535     1884042.214      442257.195
     1883866.545       442353.77     1883771.231      442427.063
#Sta/Elev= 30
       0  922.74    37.4  899.72    56.2  888.94    74.9  879.17    84.3   874.7
    93.6  870.62     103  866.94   112.4  863.83   121.9  861.78     141  859.08
   150.6  858.24   160.1  857.76   169.6  856.31   179.2  853.46   187.1  851.96
   188.7  851.66   198.3  851.68   201.6  852.74   207.8  854.72   217.4  861.44
   226.9  867.67   265.1  886.28   284.2  896.06   303.3  906.59   322.1  917.54
   340.6  928.64   359.1  940.01   377.6  951.79   396.1  964.39   433.1  990.42
#Mann= 3 , 0 , 0
       0     .08       0   187.1    .045       0   201.6      .1       0
Bank Sta=187.1,201.6
XS Rating Curve= 0 ,0
Exp/Cntr=0.3,0.1

Type RM Length L Ch R = 1 ,7097.6  ,195,195.5,195.4
XS GIS Cut Line= 2
     1884019.588      441952.775     1883668.911       442254.62
#Sta/Elev= 30
       0  964.38    19.3   949.2    28.9  941.84    38.6  934.55    57.8  921.07
    77.1  907.92    86.8  901.43    96.4   895.3     106  890.17     135  875.48
   154.2  865.49   163.9  860.54   173.5   855.5   183.2  851.74   192.8  850.24
   202.4  850.17     241  850.96   250.6   850.2   260.3  848.12   266.4 847.405
   269.9     847   279.5  846.91   280.4  847.28   289.2   850.9   308.5  866.73
   337.4  886.24   356.7  899.37   404.9  931.74   424.1  944.75   462.7  970.69
#Mann= 3 , 0 , 0
       0     .08       0   266.4    .045       0   280.4      .1       0
Bank Sta=266.4,280.4
XS Rating Curve= 0 ,0
Exp/Cntr=0.3,0.1

Type RM Length L Ch R = 1 ,6902.1  ,88.9,123.3,152.4
XS GIS Cut Line= 3
     1883900.094      441819.988        1883771.      441912.137
     1883513.809      442130.122
#Sta/Elev= 30
       0     942    37.3  919.87      56  908.92    65.3  903.65      84  893.76
   149.3   859.9   158.6  855.12   168.2  850.56   177.9     848   187.5  847.37
   197.1  847.16   206.8  846.77   235.7  845.42   245.3  844.83   254.9  844.04
   261.1 843.632   264.6   843.4   274.2  843.59   276.1 844.345   283.8   847.4
   293.5  855.11   303.1  863.06   322.4  875.17     332  881.29   351.3  893.74
   360.9  900.04   380.2  912.74   409.1  931.94   466.8   970.6   495.8   989.8
#Mann= 3 , 0 , 0
       0     .08       0   261.1    .045       0   276.1      .1       0
Bank Sta=261.1,276.1
XS Rating Curve= 0 ,0
Exp/Cntr=0.3,0.1

Type RM Length L Ch R = 1 ,6778.8  ,58.2,54.6,55.9
XS GIS Cut Line= 6
     1883887.507      441797.592     1883687.507      441919.814
     1883665.285      441901.759     1883637.507       441881.62
     1883571.571      441851.947     1883472.859      441951.961
#Sta/Elev= 30
       0  941.84    19.5  930.61    58.6  908.61    78.1  898.37    97.7  887.61
     127  870.24   136.7  864.81   146.5  859.89   156.3  855.48     166  851.66
   175.8  848.74   185.6  847.23   205.1  846.85   234.4  845.33     263  844.58
   296.3 842.741   297.3   842.7     316  842.79   325.3  843.15     344   848.1
   353.3  849.55   369.7  850.48   388.4  857.94   397.8  862.06   416.5  871.24
   425.9  876.12   444.6  886.36   463.4  897.06   482.1  908.06   510.2   925.4
#Mann= 3 , 0 , 0
       0     .08       0   296.3    .045       0     316     .08       0
Bank Sta=296.3,316
XS Rating Curve= 0 ,0
Exp/Cntr=0.3,0.1

Type RM Length L Ch R = 1 ,6724.2  ,203.9,166.5,126.1
XS GIS Cut Line= 6
     1883868.171      441793.107     1883718.692      441881.128
     1883700.463      441866.024     1883639.526      441839.982
     1883585.019      441812.117     1883496.817      441900.399
#Sta/Elev= 30
       0  932.12    19.3  921.73    38.6  911.06    57.8  900.75    67.5  895.09
    96.4  876.77     106  870.83   115.6  865.15   125.3  860.02   134.9   855.6
   144.6  851.86   154.2  848.91   163.8  847.11   173.5  846.65   226.3  845.48
   244.9  845.18   272.2  844.32     281  842.93   287.3  842.14   298.5  840.86
   307.2  840.49     316  840.56   324.7  840.29   343.9  842.23   353.5  844.93
   372.7  853.26   382.3  857.79   401.5  867.16   430.3  881.76   449.5  892.13
#Mann= 3 , 0 , 0
       0     .08       0   287.3    .045       0   307.2     .08       0
Bank Sta=287.3,307.2
XS Rating Curve= 0 ,0
Exp/Cntr=0.3,0.1

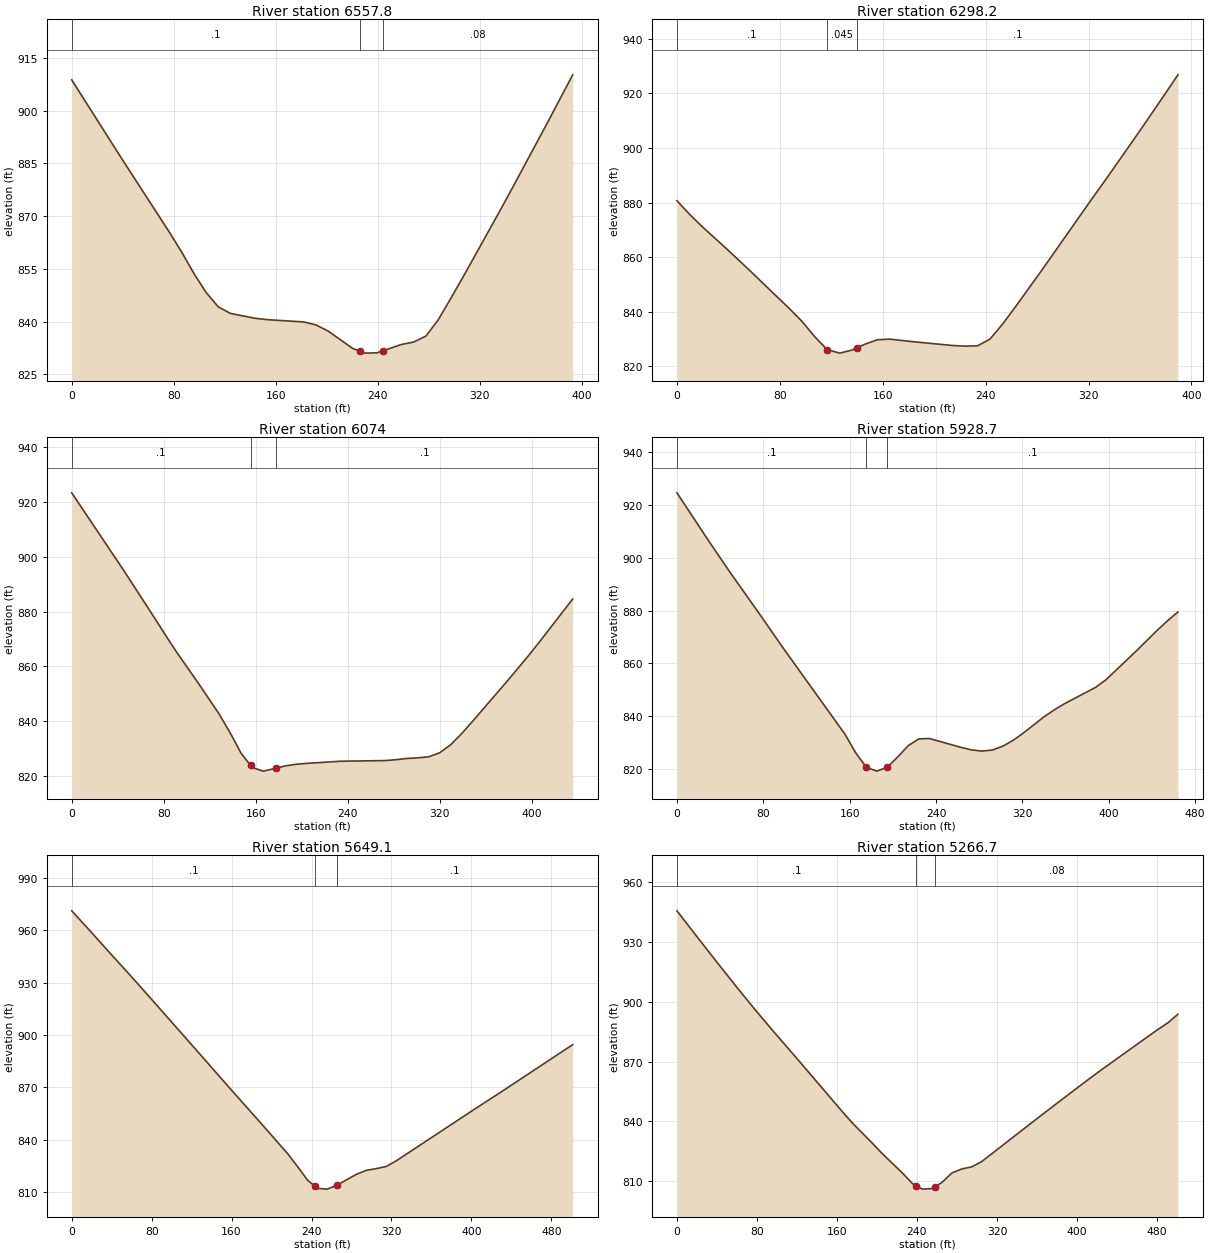
Type RM Length L Ch R = 1 ,6557.8  ,265.1,259.6,252.8
XS GIS Cut Line= 3
     1883616.391      441543.137     1883455.225      441781.049
     1883403.414      441872.968
#Sta/Elev= 28
       0  908.73    38.3  886.84    76.6   865.4    86.2  859.79    95.8  853.69
   105.4  848.27   114.9  844.18   124.5   842.3   143.7  840.93   153.3  840.53
     182  839.88   191.6  839.03   201.2  837.27   220.3  832.36   226.2 831.531
   229.9  831.01   239.5   831.1   244.2 831.686   258.6  833.48   268.2  834.16
   277.8  835.86   287.4  840.44     297  846.38   306.6  852.44   335.3  871.14
   344.9   877.5   373.7  896.93   392.9  910.16
#Mann= 3 , 0 , 0
       0      .1       0   226.2    .045       0   244.2     .08       0
Bank Sta=226.2,244.2
XS Rating Curve= 0 ,0
Exp/Cntr=0.3,0.1

Type RM Length L Ch R = 1 ,6298.2  ,220.7,224.2,226.5
XS GIS Cut Line= 2
     1883336.674      441461.246     1883210.115      441829.599
#Sta/Elev= 30
       0  880.65     9.7  875.73    19.5  871.22      39  862.88    48.7  858.62
    58.4   854.3    87.6  841.08    97.4   836.4   107.1   830.9   116.8  826.17
   126.6  824.88   136.3  826.02     140 826.821   146.1  828.14   155.8  829.77
   165.5  829.99     185  828.99   214.2  827.68     224  827.44   233.7  827.55
   243.4  830.02   253.2  835.51   262.9  841.66   282.4  854.37   321.3  880.46
   331.1   886.9   340.8  893.38   360.3  906.51   379.8  919.95   389.5  926.73
#Mann= 3 , 0 , 0
       0      .1       0   116.8    .045       0     140      .1       0
Bank Sta=116.8,140
XS Rating Curve= 0 ,0
Exp/Cntr=0.3,0.1

Type RM Length L Ch R = 1 ,6074    ,142.6,145.3,147.5
XS GIS Cut Line= 4
     1883162.095      441323.489     1883118.701       441444.13
      1883039.18      441608.196     1883022.338      441732.343
#Sta/Elev= 30
       0  923.32    45.8  894.69    73.3   876.9    82.4   870.9    91.6  865.03
   109.9  854.07   128.2   842.7   137.8  835.85   147.4  828.34   155.6  823.93
     157  823.18   166.6  821.85     178 822.915   185.8  823.76   195.4  824.36
     205  824.69   233.8  825.46   272.2  825.69   281.7     826   291.3  826.46
   300.9  826.69   310.5  827.06   320.2  828.56   329.8  831.52   339.4  835.61
   349.1   840.2     378  854.25   397.3   863.9   406.9  868.97   435.8  884.59
#Mann= 3 , 0 , 0
       0      .1       0   155.6    .045       0     178      .1       0
Bank Sta=155.6,178
XS Rating Curve= 0 ,0
Exp/Cntr=0.3,0.1

Type RM Length L Ch R = 1 ,5928.7  ,274.7,279.6,283.6
XS GIS Cut Line= 3
     1883064.092      441275.485     1882898.729      441539.764
     1882768.866      441619.496
#Sta/Elev= 30
       0  924.61    29.2  906.52    48.7   894.8    77.9  877.92    97.4  866.42
   155.9  833.07   165.6  826.17   175.4  820.72   185.1  819.25   194.8   820.7
   204.6  824.65   214.3  828.92   224.1  831.46   233.8   831.6     263  828.27
   272.8  827.29   282.5  826.84   292.3  827.23     302  828.72   311.8  830.99
   321.3  833.79   340.3  839.89   349.8   842.5   359.4  844.86   387.9  850.98
   397.5  853.87     426  864.93   445.1  872.64   454.6  876.22   464.1  879.51
#Mann= 3 , 0 , 0
       0      .1       0   175.4    .045       0   194.8      .1       0
Bank Sta=175.4,194.8
XS Rating Curve= 0 ,0
Exp/Cntr=0.3,0.1

Type RM Length L Ch R = 1 ,5649.1  ,379.7,382.4,383.7
XS GIS Cut Line= 2
     1882922.879      441073.289     1882579.455      441438.551
#Sta/Elev= 25
       0   971.2    19.7  958.86    39.3  946.35      59  933.92    68.8  927.62
    88.5   914.9   127.8  889.34   157.3  870.06   186.8  851.06   216.3  831.81
   226.1  824.48   235.9  816.84   243.4   813.2   245.8  812.03   255.6  811.58
   265.4  813.76   275.2  816.98   285.1  820.12   294.9  822.36   304.8  823.33
   314.6  824.54   324.4  827.65     403  857.36   432.5  868.34   501.4  894.45
#Mann= 3 , 0 , 0
       0      .1       0   243.4    .045       0   265.4      .1       0
Bank Sta=243.4,265.4
XS Rating Curve= 0 ,0
Exp/Cntr=0.3,0.1

Type RM Length L Ch R = 1 ,5266.7  ,227.8,232.8,237.3
XS GIS Cut Line= 2
     1882685.081      440804.933     1882311.148      441138.294
#Sta/Elev= 30
       0  945.76    19.6  933.05    39.3  920.41    58.9     908    78.6  895.85
    98.2  884.24   117.9  872.84     167     844   176.8  838.54   196.4  828.58
   206.3  823.38   225.9  813.93   235.7  808.75   239.3 807.769   245.6  806.05
   255.4  806.32   258.3  807.26   265.2  809.49     275  814.18   284.9  816.18
   294.7  817.21   304.5  819.78   363.4  842.74   402.7  857.81   422.4  865.18
   432.2  868.71   471.5  882.83   481.3   886.3   491.1  889.59     501  893.84
#Mann= 3 , 0 , 0
       0      .1       0   239.3    .045       0   258.3     .08       0
Bank Sta=239.3,258.3
XS Rating Curve= 0 ,0
Exp/Cntr=0.3,0.1

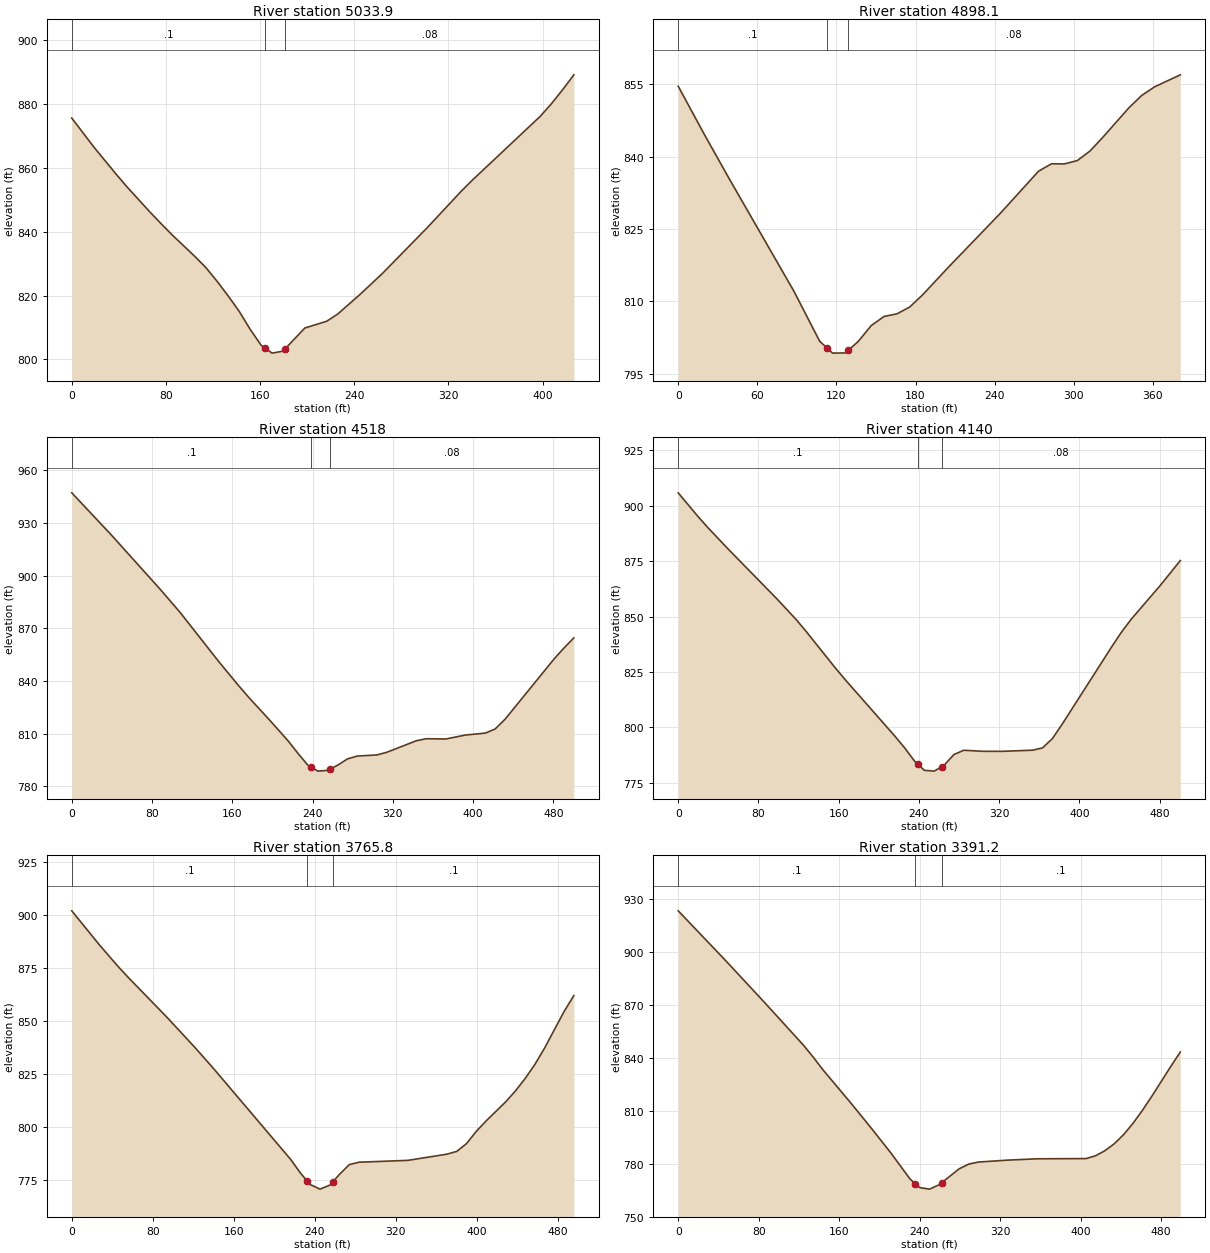
Type RM Length L Ch R = 1 ,5033.9  ,124.5,135.8,147
XS GIS Cut Line= 4
     1882504.839      440728.264     1882380.708      440776.007
     1882299.978      440822.014     1882158.485      440964.375
#Sta/Elev= 30
       0  875.56      19  866.39      38  857.86    47.5  853.79    66.5  846.12
      76  842.47    85.5  838.91   104.5  832.28     114  828.74   123.5  824.45
     133  819.82   142.3  815.03   151.6  809.42   160.9  804.44     164  803.62
   170.2  801.97   179.5   802.6   181.5 803.404     198  809.82   216.6  811.95
   225.9  814.18     245  820.37   264.2     827   302.4  841.39     331  852.69
   340.6  856.21     398  876.09   407.5  880.02   417.1  884.45   426.6   889.1
#Mann= 3 , 0 , 0
       0      .1       0     164    .045       0   181.5     .08       0
Bank Sta=164,181.5
XS Rating Curve= 0 ,0
Exp/Cntr=0.3,0.1

Type RM Length L Ch R = 1 ,4898.1  ,379.7,380.1,378.6
XS GIS Cut Line= 3
     1882441.478      440661.715     1882275.645      440665.367
      1882071.68      440733.472
#Sta/Elev= 27
       0  854.61    19.5  844.77      39  835.27    87.8  812.08   107.3  801.72
   112.7  800.36   117.1  799.25   126.8  799.29     129 799.827   136.6  801.68
   146.4  804.96   156.1  806.85   165.9   807.4   175.6  808.81   185.4  811.34
     205  817.08   244.1  828.18   273.4     837   283.2  838.53   292.9   838.5
   302.7  839.18   312.5   841.2   322.3  844.07   341.8  850.11   351.6   852.7
   361.4  854.49   380.9  856.98
#Mann= 3 , 0 , 0
       0      .1       0   112.7    .045       0     129     .08       0
Bank Sta=112.7,129
XS Rating Curve= 0 ,0
Exp/Cntr=0.3,0.1

Type RM Length L Ch R = 1 ,4518    ,382.1,378,373.2
XS GIS Cut Line= 2
     1882513.577      440281.237     1882013.623      440304.911
#Sta/Elev= 30
       0   947.1    39.3   923.2    88.3  892.08     108  879.01   147.2  850.53
   166.8     837   176.6  830.51   196.3   818.3   215.9  805.71   225.7  798.62
   235.5  791.92   238.8 790.826   245.4  788.64   255.2  789.08   257.8  789.85
     265     792   274.8  795.58   284.6  797.22   304.2  797.86     314  799.36
   343.5  805.93   353.3  807.09   372.9  806.94   392.6   809.2   412.2  810.28
     422  812.62   431.8  818.08   480.9  852.57   490.7  858.76   500.5   864.5
#Mann= 3 , 0 , 0
       0      .1       0   238.8    .045       0   257.8     .08       0
Bank Sta=238.8,257.8
XS Rating Curve= 0 ,0
Exp/Cntr=0.3,0.1

Type RM Length L Ch R = 1 ,4140    ,376.5,374.2,371
XS GIS Cut Line= 2
     1882430.598      439864.645     1881944.852      439985.832
#Sta/Elev= 30
       0  905.85    19.6  895.22    29.4  890.22    49.1   880.8    98.2  858.07
   117.8  848.54   127.6  843.25   157.1  826.53   166.9  821.29     216  796.02
   225.8  790.69   235.6  784.75   238.7 783.431   245.4  780.58   255.2  780.22
   262.7 782.209     265  782.82   274.9  787.72   284.7  789.64   304.3  789.15
   323.9  789.17   353.4  789.67   363.2   790.7     373  794.87   382.8   801.4
   431.9  836.13   441.7  842.81   451.6  848.76     481  864.25   500.6  875.28
#Mann= 3 , 0 , 0
       0      .1       0   238.7    .045       0   262.7     .08       0
Bank Sta=238.7,262.7
XS Rating Curve= 0 ,0
Exp/Cntr=0.3,0.1

Type RM Length L Ch R = 1 ,3765.8  ,370.7,374.7,378.3
XS GIS Cut Line= 3
     1882347.982      439500.659     1882183.115      439533.377
     1881877.062      439650.618
#Sta/Elev= 30
       0  902.07      28  885.57    46.7  875.25      56  870.47    93.4  852.05
   121.4  837.59   140.1  827.46   216.3  784.46   225.9  778.05   232.6 774.292
   235.6  772.61   245.2  770.49   254.8  772.37   257.8 773.966   264.5  777.53
   274.1  782.09   283.8  783.22     332  784.09   370.5  787.02   380.2  788.33
   389.8  792.01   399.4  797.77   409.1  802.71   428.4  811.71     438  816.84
   447.6  822.72   457.3  829.42   466.9  837.18   486.2   854.5   495.8  861.99
#Mann= 3 , 0 , 0
       0      .1       0   232.6    .045       0   257.8      .1       0
Bank Sta=232.6,257.8
XS Rating Curve= 0 ,0
Exp/Cntr=0.3,0.1

Type RM Length L Ch R = 1 ,3391.2  ,373.1,375,376.9
XS GIS Cut Line= 4
     1882308.919      439163.203     1882099.045      439184.784
      1881908.49      439222.687     1881815.213      439231.562
#Sta/Elev= 30
       0  923.04      48  894.35    86.3  870.87   124.7  846.87   134.3  840.16
   143.8  833.12   172.6  813.59   191.8  800.12     211  786.31   230.4  771.29
   235.8  768.59   240.1  766.44   249.8  765.58   259.6  768.14     262 769.273
     279  776.99   288.7  779.74   298.4   780.9   327.6  781.99   356.7  782.74
   405.3  782.86   414.6  784.42     424  787.29   433.4  791.26   442.8   796.5
   452.1   802.9   461.5  810.27   470.9   818.3   489.6  835.06     499  843.15
#Mann= 3 , 0 , 0
       0      .1       0   235.8    .045       0     262      .1       0
Bank Sta=235.8,262
XS Rating Curve= 0 ,0
Exp/Cntr=0.3,0.1

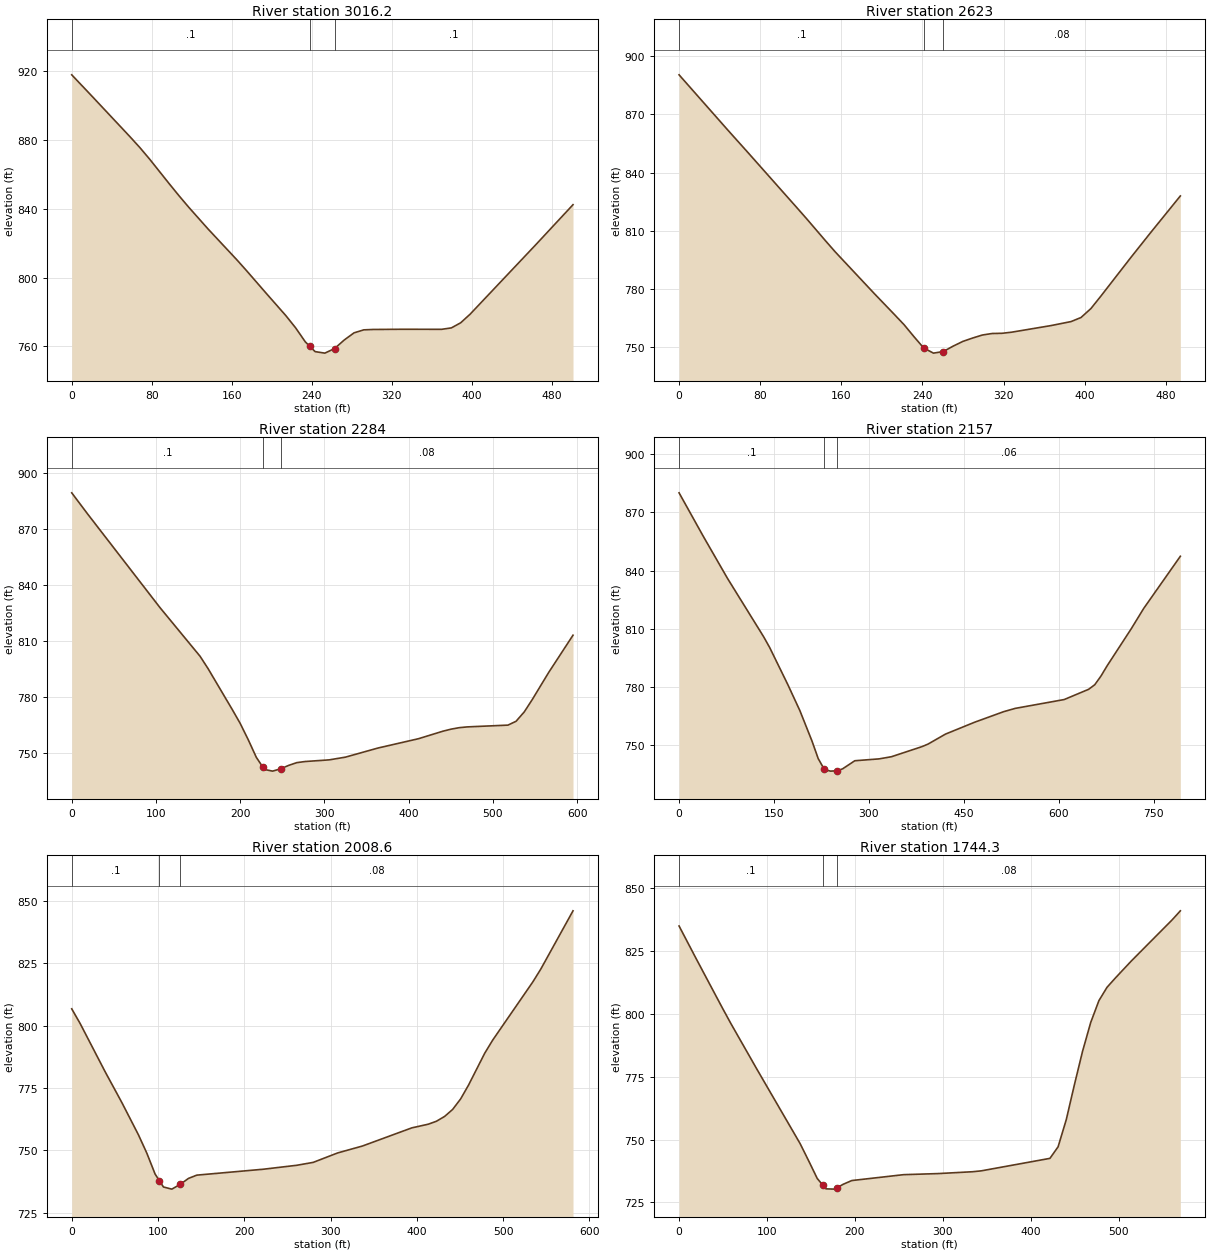
Type RM Length L Ch R = 1 ,3016.2  ,387.9,393.1,397.9
XS GIS Cut Line= 3
     1882251.047      438794.208     1881874.001      438837.217
     1881754.449      438859.383
#Sta/Elev= 30
       0  917.88    19.5  905.92    58.4  881.79    68.1  875.58    77.8  868.91
    97.3  854.68     107  847.74   116.8  841.01   136.2  828.31   165.4  810.12
   175.2  803.72   194.6  790.73   214.1  777.84   223.8  770.78   233.5  762.63
   237.8 760.138   243.3  756.95     253  756.07   262.7   758.7   272.4   763.7
   282.2  767.86   291.9   769.6   301.6  769.83   330.8  769.94   369.8  769.91
   379.5  770.74   388.8   773.7   398.2  778.69   463.7  818.99   501.1  842.37
#Mann= 3 , 0 , 0
       0      .1       0   237.8    .045       0   262.7      .1       0
Bank Sta=237.8,262.7
XS Rating Curve= 0 ,0
Exp/Cntr=0.3,0.1

Type RM Length L Ch R = 1 ,2623    ,335.5,339,341.7
XS GIS Cut Line= 3
     1882186.572      438467.863      1881841.18      438430.379
      1881694.77      438443.802
#Sta/Elev= 29
       0  890.46    48.2  861.88    67.6  850.56   115.8  822.14   125.5  816.38
   144.8   804.6   154.4  798.88     193  777.33   212.3  766.83     222  761.47
   231.6  755.39   241.3  749.48   250.9  746.85   260.6  747.65   270.2  750.43
   279.9   752.9   289.5  754.63   299.2   756.2   308.8  756.98   318.5  757.08
   328.1  757.66     367  761.08   386.6  763.13   396.4  765.22   406.2  769.85
     416  776.26   445.4  796.08     465  808.98   494.4  827.96
#Mann= 3 , 0 , 0
       0      .1       0   241.3    .045       0   260.6     .08       0
Bank Sta=241.3,260.6
XS Rating Curve= 0 ,0
Exp/Cntr=0.3,0.1

Type RM Length L Ch R = 1 ,2284    ,111,127,142.8
XS GIS Cut Line= 4
     1882231.879      438240.894     1882057.869      438124.219
     1881955.234      438098.562     1881689.345      438185.555
#Sta/Elev= 30
       0  889.15      19  877.77   104.8  827.78   152.4  801.77   161.9  795.16
   190.5  773.38     200   765.9   209.5  757.23   219.1  747.81     227 742.451
   228.7   741.3   238.4   740.4     248  741.62   257.6  743.48   267.2  744.94
   276.8  745.52   305.7  746.42     325  747.88   363.5  752.74   411.8  757.74
   440.7  761.75   450.4  762.84     460  763.62   469.6  764.04   517.9  764.99
   527.5  767.05   537.2  772.04   546.8  778.71   566.1  793.05   595.1  813.05
#Mann= 3 , 0 , 0
       0      .1       0     227    .045       0     248     .08       0
Bank Sta=227,248
XS Rating Curve= 0 ,0
Exp/Cntr=0.3,0.1

Type RM Length L Ch R = 1 ,2157    ,142.2,148.4,154.6
XS GIS Cut Line= 5
     1882255.751      438197.491     1882120.117      438036.901
     1882012.695      437888.246     1881933.485      437775.399
     1881673.069      437791.675
#Sta/Elev= 30
       0  880.15    38.2  857.74    76.4  836.05   133.8  805.77   143.3  800.22
     172  781.07   191.1  767.58   210.2  751.91   219.9  742.95   229.5  737.38
   239.2  736.44     250 736.639   258.5  737.62   277.8   741.8   316.4  742.77
   335.7  743.88     384  749.09   393.6  750.41   421.2  755.57   467.1  761.68
   513.1  767.14   531.5  768.85   608.8   773.4   647.4  778.69   657.1  781.05
   666.8  785.47   676.4   790.7   715.1  810.12   734.4  820.42   792.4  847.39
#Mann= 3 , 0 , 0
       0      .1       0   229.5    .045       0     250     .06       0
Bank Sta=229.5,250
XS Rating Curve= 0 ,0
Exp/Cntr=0.3,0.1

Type RM Length L Ch R = 1 ,2008.6  ,267.5,264.3,260.3
XS GIS Cut Line= 4
     1882263.586      438037.503     1882177.634      437801.438
     1882039.796      437684.284     1882021.376      437536.684
#Sta/Elev= 30
       0  806.74     9.7  800.88    38.6  781.57      58  769.19    77.3  756.19
      87  748.85    96.6  740.45   101.7 737.708   106.3  735.24     116  734.39
   125.6  736.27   135.3  738.69   144.9     740   222.2  742.38   260.8  743.96
   279.8  745.12   308.4  748.94   336.9  751.69     394  758.96   413.1  760.44
   422.6  761.62   432.1  763.56   441.4  766.36   450.7   770.6     460  776.25
   478.6  788.93   487.9  794.23   534.4  817.57   543.7  822.77   580.9  846.07
#Mann= 3 , 0 , 0
       0      .1       0   101.7    .045       0   125.6     .08       0
Bank Sta=101.7,125.6
XS Rating Curve= 0 ,0
Exp/Cntr=0.3,0.1

Type RM Length L Ch R = 1 ,1744.3  ,140,139.2,138.4
XS GIS Cut Line= 3
     1882534.911      437948.344     1882334.029      437588.097
     1882281.713      437439.477
#Sta/Elev= 30
       0   834.9    19.6   821.8    49.1   802.4    58.9  796.12    88.4  778.02
   137.5  748.46   147.3  741.58   157.1  734.51   163.3  731.92     167  730.38
   176.8  730.27     180 730.894   186.6  732.19   196.4  733.68   255.3  736.02
   294.6  736.45   333.9  737.19   343.7  737.54   421.7   742.5     431   747.1
   440.3  757.92   449.5  771.73   458.8  785.08   468.1  796.56   477.4  805.21
   486.6  810.51   495.9  814.14   514.4  821.04   560.8  837.38     570  840.93
#Mann= 3 , 0 , 0
       0      .1       0   163.3    .045       0     180     .08       0
Bank Sta=163.3,180
XS Rating Curve= 0 ,0
Exp/Cntr=0.3,0.1

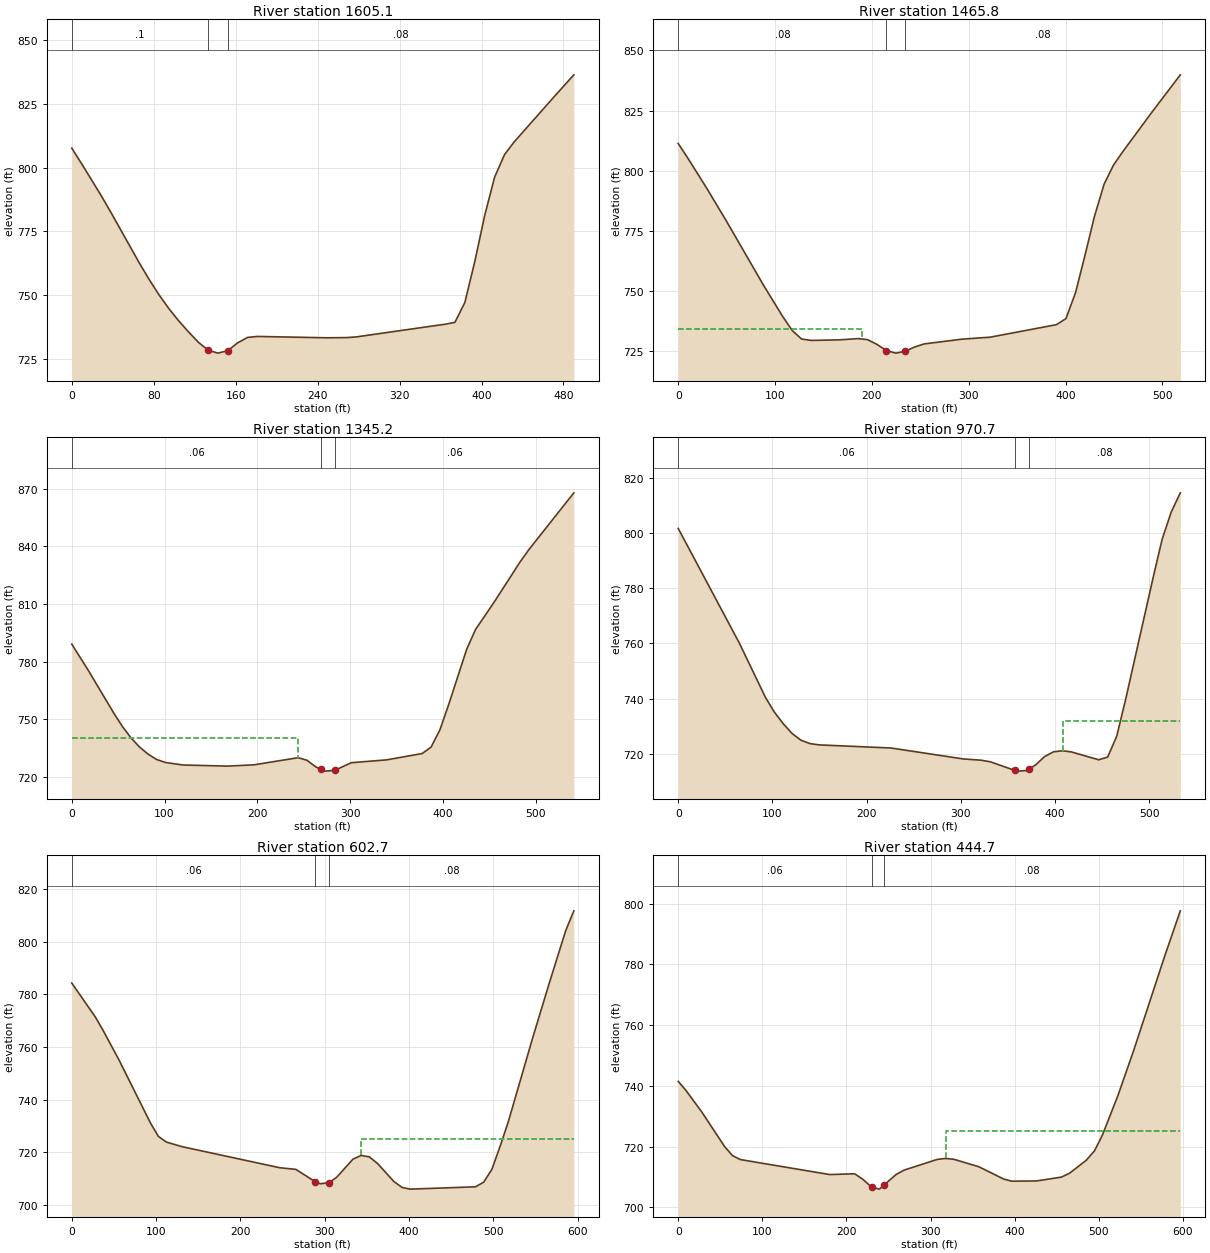
Type RM Length L Ch R = 1 ,1605.1  ,145.2,139.3,132.8
XS GIS Cut Line= 4
     1882625.825      437857.416     1882590.234      437759.587
     1882449.659      437529.149     1882409.896      437420.133
#Sta/Elev= 30
       0  807.58     9.5  801.56    28.4  789.19    37.9  782.64    66.2  762.41
    75.7  756.03    85.2  750.09    94.6  744.82   104.1  740.04   113.7  735.71
   123.4  731.59     133  728.42   142.7  727.26   152.3  728.22   161.9  731.29
   171.6  733.41   181.2   733.8   248.7  733.27     268  733.34   277.6  733.61
   364.4  738.59     374  739.31   383.7   747.1   393.4  763.12     403  781.07
   412.7  796.13   422.4  805.05     432   810.1   470.7  827.66   490.1  836.32
#Mann= 3 , 0 , 0
       0      .1       0     133    .045       0   152.3     .08       0
Bank Sta=133,152.3
XS Rating Curve= 0 ,0
Exp/Cntr=0.3,0.1

Type RM Length L Ch R = 1 ,1465.8  ,124.2,120.6,116.9
XS GIS Cut Line= 4
     1882773.394      437805.332     1882737.111      437693.368
      1882559.51      437527.115     1882509.722      437377.815
#Sta/Elev= 30
       0  811.28     9.8  805.26    29.4  792.69      49  779.53    88.3  752.16
   107.9   739.3   117.7  733.49   127.4  729.94   137.2  729.37   166.4   729.6
   185.8  730.12   195.5  729.68   205.3  727.69     215  725.11   224.7  724.08
   234.5  724.87   244.2  726.65   253.9  727.91   292.8  729.88     322  730.71
   390.5  735.92   400.3  738.43   410.2  749.19     420  764.81   429.8  781.01
   439.7  794.37   449.5  802.37   459.3  808.04   488.8  824.15   518.4  839.85
#Mann= 3 , 0 , 0
       0     .08       0     215    .045       0   234.5     .08       0
#XS Ineff= 2 , 0
       0     190     734               0
Permanent Ineff=
       F       F
Bank Sta=215,234.5
XS Rating Curve= 0 ,0
Exp/Cntr=0.3,0.1

Type RM Length L Ch R = 1 ,1345.2  ,365.2,374.5,381.9
XS GIS Cut Line= 4
     1882913.368      437709.846      1882881.39      437624.428
     1882643.725       437464.61     1882595.443      437308.371
#Sta/Elev= 30
       0  789.12    18.2  775.15    45.6  752.93    54.7  746.14    63.8   740.3
      73  735.54    82.1  731.86    91.2  729.08   100.8  727.48   119.8  726.15
   167.6  725.57   196.2  726.23     244  729.96   253.5  728.62     263  725.17
   268.5   723.9   272.6  722.96   283.5  723.38   301.2  727.34   339.4  728.83
   377.6  732.12   387.2  735.44   396.8   744.5   406.5  758.07   425.7  786.56
   435.3  796.86   454.6  810.55   483.4  832.11     493  838.58   541.1  867.94
#Mann= 3 , 0 , 0
       0     .06       0   268.5    .045       0   283.5     .06       0
#XS Ineff= 2 , 0
       0     244     740               0
Permanent Ineff=
       F       F
Bank Sta=268.5,283.5
XS Rating Curve= 0 ,0
Exp/Cntr=0.3,0.1

Type RM Length L Ch R = 1 ,970.7   ,368.1,368,366.9
XS GIS Cut Line= 4
     1883198.676       437640.85     1883177.538      437522.091
     1882978.435       437240.44     1882932.834      437190.547
#Sta/Elev= 30
       0  801.74      65  760.06    92.8   740.3   102.1  735.08   111.4   730.9
   120.6  727.41   130.2   724.9   139.8  723.66   149.4  723.19     226  722.05
   302.7  718.08   321.8  717.62   331.4  717.04   357.5  713.92   360.2  713.66
   369.7  713.86   372.5  714.44   379.3  715.85   388.9  718.92   398.5  720.68
   408.1  721.04   417.6  720.62   446.4  717.78     456  718.77   465.6  726.34
   475.2  739.92   504.2  783.87   513.8  797.81   523.5  807.75   533.1  814.68
#Mann= 3 , 0 , 0
       0     .06       0   357.5    .045       0   372.5     .08       0
#XS Ineff= 2 , 0
       0                   408.1       0     732
Permanent Ineff=
       F       F
Bank Sta=357.5,372.5
XS Rating Curve= 0 ,0
Exp/Cntr=0.3,0.1

Type RM Length L Ch R = 1 ,602.7   ,162,158,153.5
XS GIS Cut Line= 4
     1883537.321      437307.615     1883416.209      437219.796
     1883195.781      436925.013     1883120.203      436906.204
#Sta/Elev= 30
       0  784.28      28  771.36    37.4  766.16    56.1  754.99    93.5  730.99
   102.8  725.97   112.2  723.83   130.9  722.07   246.5  714.08   265.8  713.44
   288.5 708.807   294.9  707.98   305.5  708.39   314.3  710.46   333.6  717.32
   343.3  718.75     353  718.18   362.7  715.69   382.1  708.84   391.8  706.58
   401.4  705.93   478.9  706.81   488.6  708.56   498.3   713.4     508  722.09
   517.7  731.38   546.9  763.59   566.4  784.19   585.8  804.07   595.6  811.75
#Mann= 3 , 0 , 0
       0     .06       0   288.5    .045       0   305.5     .08       0
#XS Ineff= 2 , 0
       0                   343.3       0     725
Permanent Ineff=
       F       F
Bank Sta=288.5,305.5
XS Rating Curve= 0 ,0
Exp/Cntr=0.3,0.1

Type RM Length L Ch R = 1 ,444.7   ,155.7,150.6,145.3
XS GIS Cut Line= 4
     1883579.771      437183.521     1883545.417      437088.097
     1883254.833      436823.037     1883153.562      436809.956
#Sta/Elev= 30
       0  741.49     9.2  738.49    27.7  731.54    55.3  719.97    64.5  717.06
    73.8  715.76   180.1  710.82   209.6  711.08   219.4  709.28     230 706.649
   239.1  706.03   244.4  707.31   258.8  710.82   268.6   712.3   307.9  715.81
   317.7  716.12   327.6  715.85   357.1  713.42   386.6  709.38   396.4  708.64
   425.9  708.72   455.4  709.98   465.2  711.28   484.9   715.5   494.7  718.59
     504  723.67   522.6  736.78   541.2  751.52   578.3  782.75   596.8  797.61
#Mann= 3 , 0 , 0
       0     .06       0     230    .045       0   244.4     .08       0
#XS Ineff= 2 , 0
       0                   317.7       0     725
Permanent Ineff=
       F       F
Bank Sta=230,244.4
XS Rating Curve= 0 ,0
Exp/Cntr=0.3,0.1