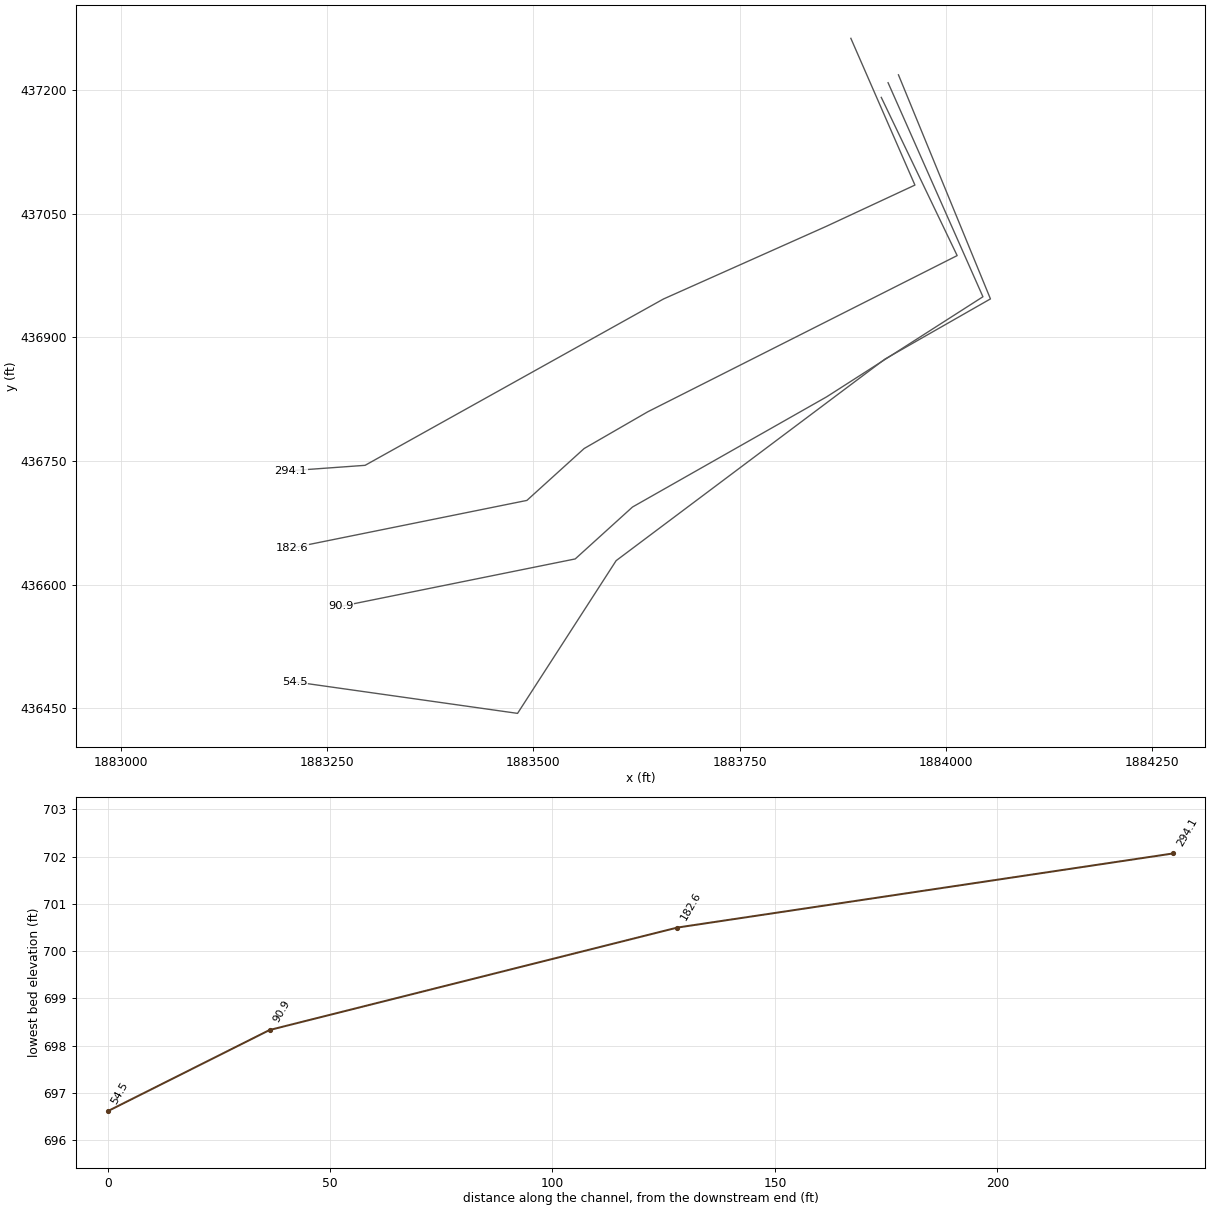
HEC-RAS study BULLPUSHFK.prj: BULLPUSHFK

--- BULLPUSHFK.g01 (geometry) --- (continued)

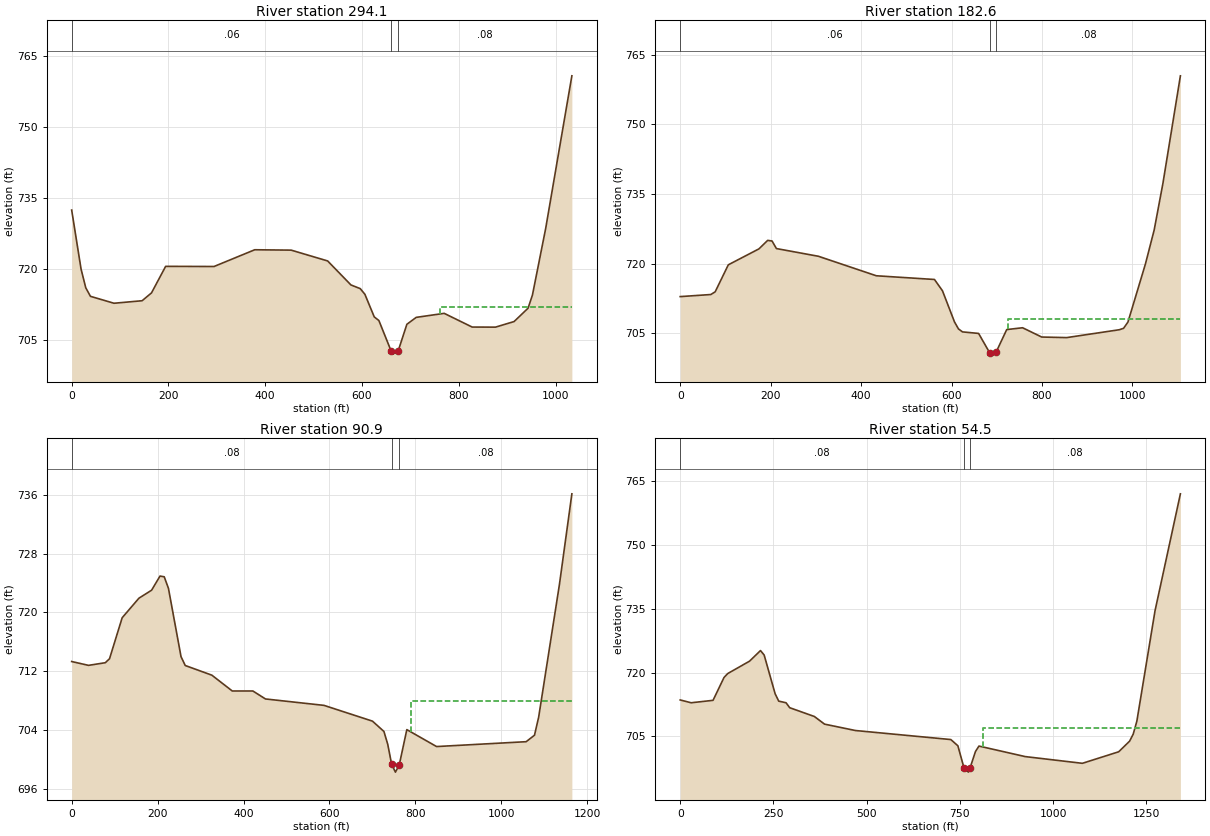
Type RM Length L Ch R = 1 ,294.1   ,111,111.5,111.7
XS GIS Cut Line= 6
     1883884.925      437262.595     1883962.616      437084.644
     1883855.498      437034.774     1883657.662      436946.497
     1883295.873      436744.809     1883205.585       436738.29
#Sta/Elev= 30
       0  732.45    19.4  720.01    29.1  716.06    38.8  714.26    87.4   712.8
   145.6  713.33     165  714.99   194.2  720.58   294.2  720.55   378.3  724.08
   453.6     724     529  721.72   577.1  716.66   596.4  715.88     606  714.68
   625.3  709.92   634.9  709.15   659.9   702.8   663.8  702.07   674.9  702.79
   692.7  708.36     712  709.82   769.8  710.67   827.6  707.78   875.8  707.76
   914.3  708.94   943.2  711.76   952.2  714.53   979.4  728.48  1033.7  760.76
#Mann= 3 , 0 , 0
       0     .06       0   659.9    .045       0   674.9     .08       0
#XS Ineff= 2 , 0
       0                   760.2       0     712
Permanent Ineff=
       F       F
Bank Sta=659.9,674.9
XS Rating Curve= 0 ,0
Exp/Cntr=0.3,0.1

Type RM Length L Ch R = 1 ,182.6   ,91.5,91.7,91.4
XS GIS Cut Line= 6
     1883921.817      437190.981     1884013.831       436999.14
     1883638.563      436809.687     1883561.523      436765.199
     1883492.079      436702.265     1883207.791      436644.757
#Sta/Elev= 30
       0  712.89    67.7  713.34    77.4  713.93   106.4  719.74   174.1  723.17
   193.4     725   203.1  724.87   212.8  723.24   305.6  721.58   433.7  717.38
   562.3  716.58     580  714.15   606.6  707.44   615.4  705.93   624.3  705.29
   659.9  704.96     685 700.687   686.6   700.5   699.2  701.05   722.1  705.79
   757.2  706.18   799.5  704.18   854.8  704.06   970.8  705.75   980.5  706.06
   990.2  707.41  1028.8   719.9  1048.2  727.24  1067.5  737.26  1106.2  760.45
#Mann= 3 , 0 , 0
       0     .06       0     685    .045       0   699.2     .08       0
#XS Ineff= 2 , 0
       0                     725       0     708
Permanent Ineff=
       F       F
Bank Sta=685,699.2
XS Rating Curve= 0 ,0
Exp/Cntr=0.3,0.1

Type RM Length L Ch R = 1 ,90.9    ,33.7,36.4,39.5
XS GIS Cut Line= 6
     1883930.064      437208.776     1884045.081      436949.227
     1883855.498       436827.83     1883620.117      436694.236
     1883550.673      436631.302     1883266.385      436573.793
#Sta/Elev= 30
       0  713.34    39.2  712.82    78.3  713.18    88.1  713.72   117.5  719.28
   156.6  721.94     186  723.02   205.6  724.94   215.4  724.84   225.2  723.28
   254.5     714   264.3   712.8   326.2  711.49   373.8  709.34   421.8  709.34
     451  708.26   587.2  707.39     700  705.25   726.7  703.85   735.6   702.1
   744.5  699.43   753.4  698.33   762.3  699.29     780   704.1   849.2   701.8
  1057.7  702.46  1077.1  703.34  1086.8  705.79  1135.1  723.78  1164.1   736.1
#Mann= 3 , 0 , 0
       0     .08       0   744.5    .045       0   762.3     .08       0
#XS Ineff= 2 , 0
       0                   788.8       0     708
Permanent Ineff=
       F       F
Bank Sta=744.5,762.3
XS Rating Curve= 0 ,0
Exp/Cntr=0.3,0.1

Type RM Length L Ch R = 1 ,54.5    ,50.9,54.5,57.9
XS GIS Cut Line= 6
     1883942.651      437218.324     1884054.196      436946.623
     1883926.331      436873.663     1883600.307      436629.232
     1883480.758      436444.019     1883210.793      436482.213
#Sta/Elev= 30
       0  713.56    29.4   712.9    88.1  713.47   117.5  718.83   127.3  719.75
     186  722.67   215.4  725.16   225.2  724.11   254.6  715.02   264.3  713.28
   283.9   712.9   293.7  711.74   359.8  709.68   387.2  707.88   470.1  706.38
   725.9  704.26   744.8   702.8   761.3  697.58   773.1  696.61     777 697.476
     792  701.45   801.4  702.73   925.3  700.26  1078.8  698.68  1176.2  701.39
  1205.4  703.88  1215.1  705.53  1224.9  708.58  1273.6  734.49  1341.7  761.97
#Mann= 3 , 0 , 0
       0     .08       0   761.3    .045       0     777     .08       0
#XS Ineff= 2 , 0
       0                   810.9       0     707
Permanent Ineff=
       F       F
Bank Sta=761.3,777
XS Rating Curve= 0 ,0
Exp/Cntr=0.3,0.1

Chan Stop Cuts=-1
Use User Specified Reach Order=0
Composite Channel Slope=5